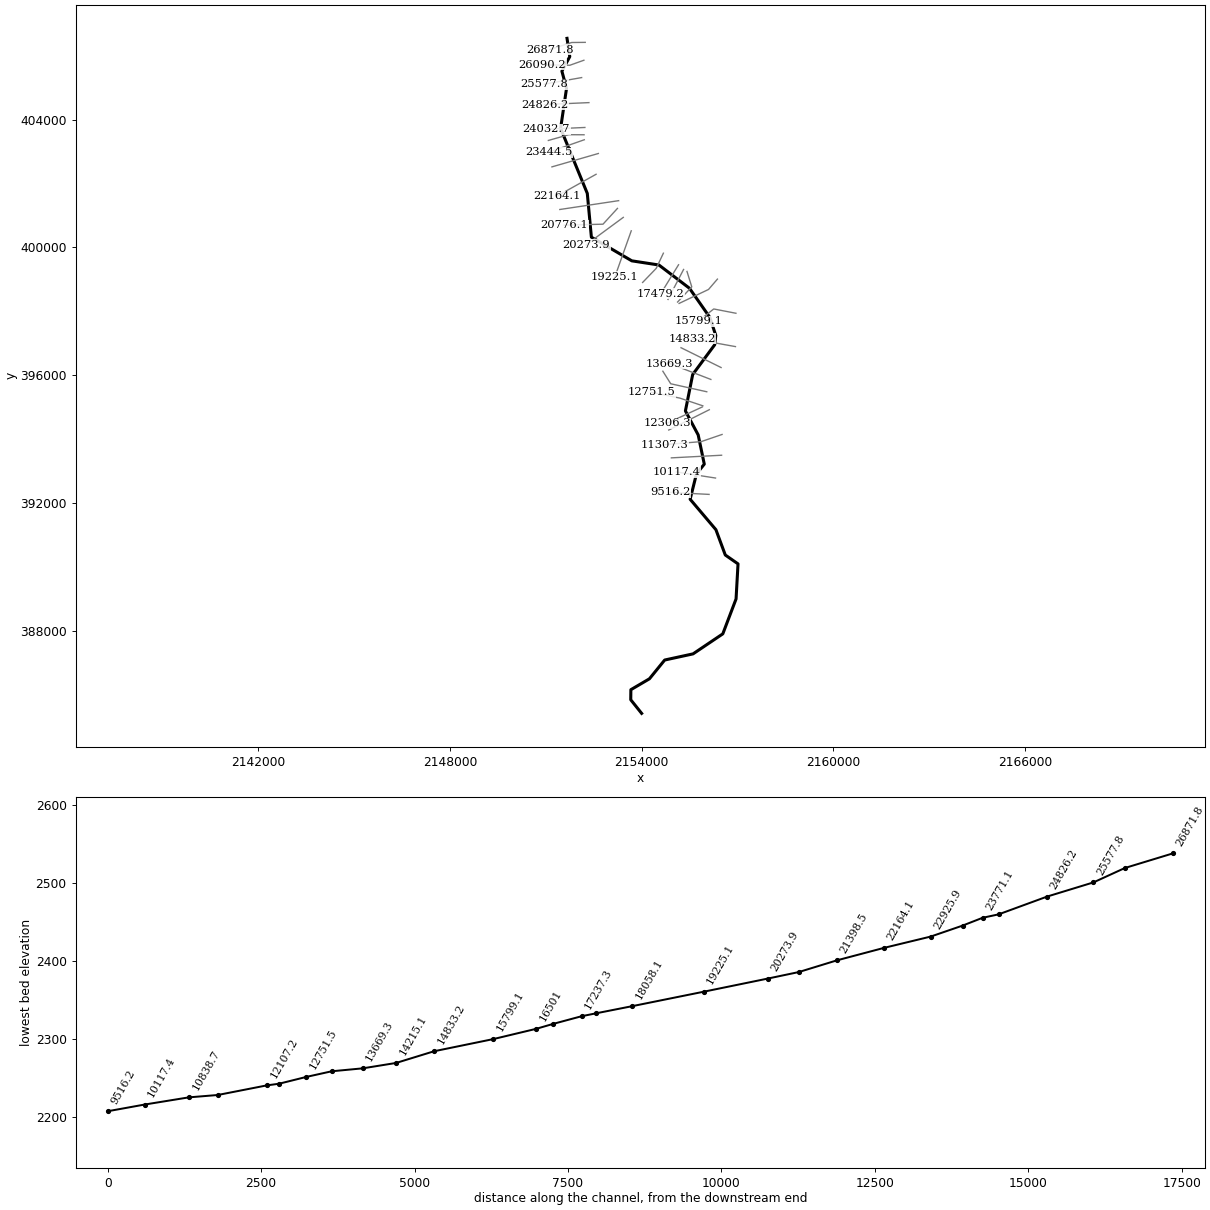
--- RobbinsRun.prj (project) ---

Proj Title=RobbinsRun
Current Plan=p01
Geom File=g01
Flow File=f01
Plan File=p01
DSS Export Rating Curves=0
DSS Export Rating Curve Sorted=0
DSS Export Volume Flow Curves=0
DXF OffsetX=0
DXF OffsetY=0
DXF ScaleX=0
DXF ScaleY=0

--- RobbinsRun.p01 (plan) ---

Plan Title=Floodplain
Program Version=4.00
Geom File=g01
Flow File=f01
K Sum by GR=0
Std Step Tol=0.01
Critical Tol=0.01
Num of Std Step Trials=20
Max Error Tol=0.3
Flow Tol Ratio=0.001
Split Flow NTrial=30
Split Flow Tol=0.02
Split Flow Ratio=0.02
Log Output Level=0
Friction Slope Method=1
Unsteady Friction Slope Method=2
Unsteady Bridges Friction Slope Method=1
Global Log Level=0
CheckData=False
Run HTab=0
Run UNet=0
Run PostProcess=0
UNET Theta=0
UNET Theta Warmup=0
UNET ZTol=0
UNET ZSATol=0
UNET MxIter=0
UNET MaxInSteps=0
UNET DtIC=0
UNET DtMin=0
UNET MaxCRTS=0
UNET WFStab=0
UNET SFStab=0
UNET WFX=0
UNET SFX=0
UNET DSS MLevel=0
UNET DZMax Abort=0
UNET Convert EG Bridges=0
UNET Use Existing IB Tables=0
UNET Froude Limit=0
UNET Froude Power=0
Write IC File=0
Echo Input=False
Echo Output=False
Write Detailed=0

--- RobbinsRun.f01 (steady flow) ---

Flow Title=NFF Regression Equation
Program Version=4.00
Number of Profiles=1
Profile Names=P100yr
River Rch & RM=RobbinsRun,Main      ,26871.8
1088.336
River Rch & RM=RobbinsRun,Main      ,24032.7
1154.810
River Rch & RM=RobbinsRun,Main      ,21398.5
1265.195
River Rch & RM=RobbinsRun,Main      ,16501
1335.825
River Rch & RM=RobbinsRun,Main      ,15799.1
1684.081
River Rch & RM=RobbinsRun,Main      ,10838.7
1846.910
River Rch & RM=RobbinsRun,Main      ,298.6
2048.849
Boundary for River Rch & Prof#=RobbinsRun,Main      ,1
Up Type=0
Dn Type=3
Dn Slope=0.014013

--- RobbinsRun.g01 (geometry) ---

Geom Title=USGS 10m DEM
Program Version=4.10

River Reach=RobbinsRun      ,Main
Reach XY= 30
     2151660.617      406538.581      2151746.97      405966.784
     2151500.096      405512.096     2151645.408      404973.033
     2151460.217      403722.007     2152295.408      401688.658
     2152423.456      400319.871     2153689.158      399579.284
     2154537.171      399449.211     2155493.777      398721.789
     2156130.358      397811.553     2156317.858      397245.928
     2156283.483      396955.303      2155594.42      396024.053
     2155366.295      394884.991     2155766.296      394134.991
     2155956.921      393220.928     2155711.976      392913.312
     2155514.733      392122.491     2156320.983      391170.928
     2156614.733      390378.741     2157013.371      390101.049
     2156951.846      389004.422     2156536.919      387912.717
     2155605.672      387286.636     2154717.739      387094.185
     2154240.795      386507.479     2153659.012      386165.891
     2153655.483      385851.439     2153996.372      385425.688

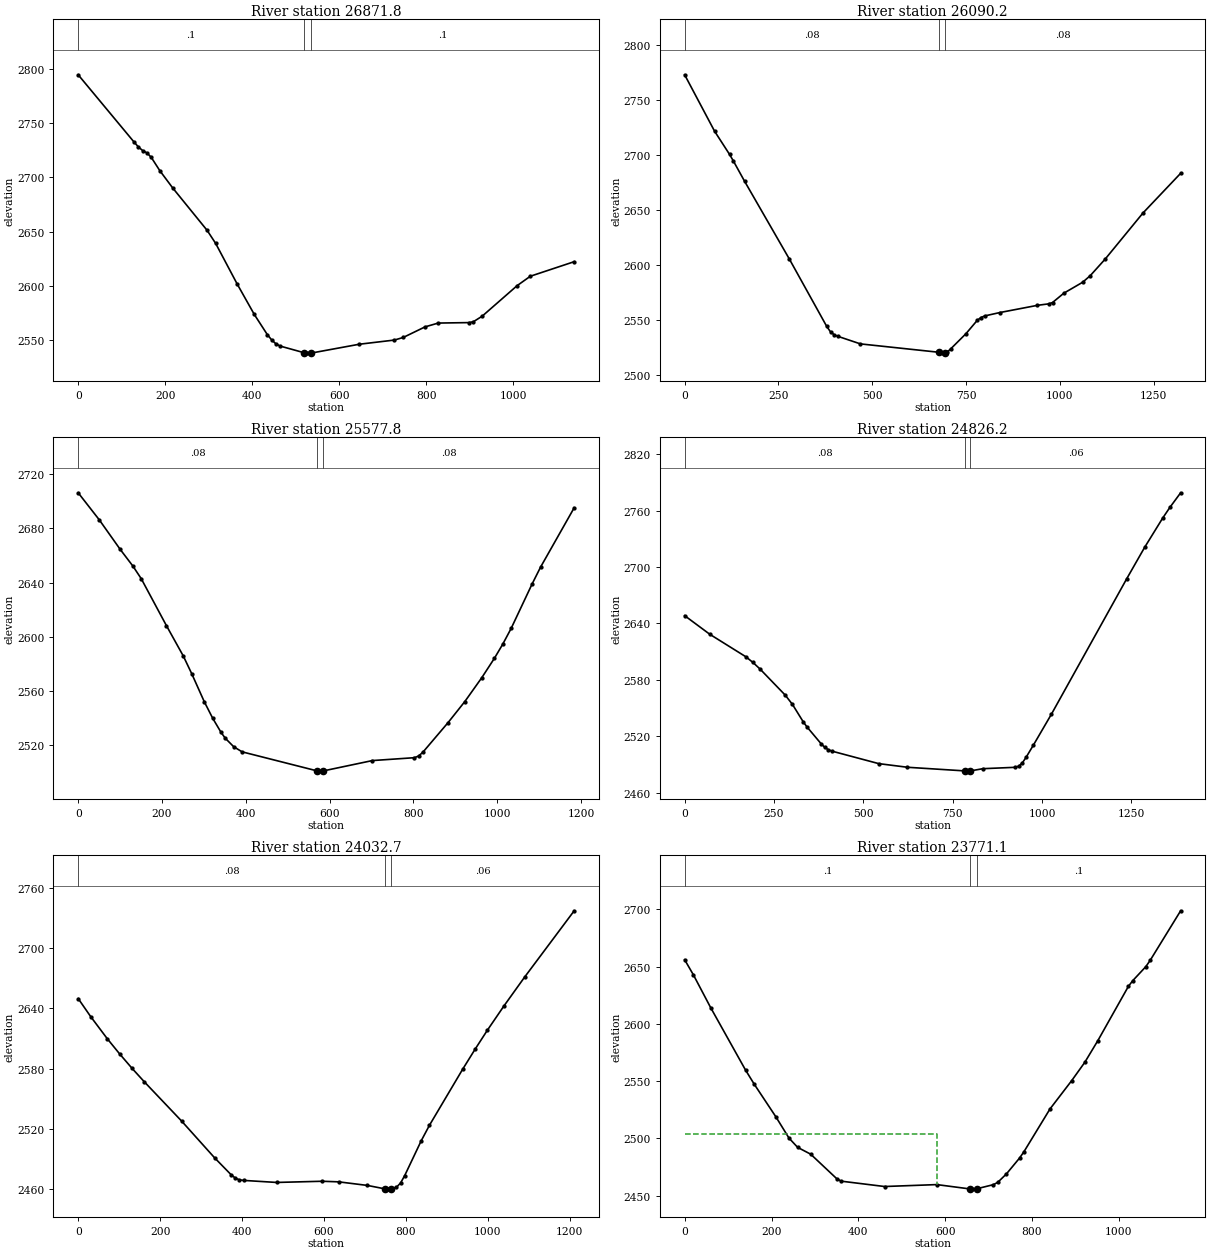
Type RM Length L Ch R = 1 ,26871.8 ,788.9,781.7,774.3
XS GIS Cut Line= 3
     2152231.047      406412.471     2151806.712       406408.27
     2151126.093      406188.837
#Sta/Elev= 30
       0 2794.45   128.3 2732.59   138.2 2728.14     148 2724.76   157.9 2722.62
   167.8 2718.51   187.5 2706.24   217.1 2690.35   296.1 2651.38   315.8 2639.32
   365.1 2602.05   404.6 2573.92   434.4 2555.46   444.5 2550.49   454.6 2546.79
   464.6 2544.77   519.1 2538.71   525.1 2538.35   535.2 2538.39   645.9 2546.54
   726.5 2550.38   746.7 2552.76     797 2562.52   827.2 2566.02   897.7 2566.44
   907.8 2567.22     928 2572.29  1008.5 2600.46  1038.8  2609.1  1139.5 2622.49
#Mann= 3 , 0 , 0
       0      .1       0   519.1    .045       0   535.2      .1       0
Bank Sta=519.1,535.2
XS Rating Curve= 0 ,0
Exp/Cntr=0.3,0.1

Type RM Length L Ch R = 1 ,26090.2 ,508.8,512.3,516
XS GIS Cut Line= 3
     2152189.034      405853.694     2151747.894      405696.144
     2150894.773      405710.343
#Sta/Elev= 30
       0 2773.23    79.7 2721.84   119.6  2700.7   129.6  2694.8   159.5 2676.31
   279.1 2605.26   378.7 2543.86   388.7 2538.96   398.7 2536.27   408.6 2534.86
   468.4    2528   677.8 2520.36   689.3 2519.59   692.8  2519.9   699.3 2520.47
   709.3 2523.58   749.5 2537.26   779.6 2549.42   789.6 2552.05   799.7  2553.5
   839.8 2556.57   940.2 2563.16   970.3 2564.51   980.4 2565.72  1010.5 2574.22
  1060.7 2584.21  1080.8 2590.17  1120.9  2605.4  1221.3 2647.27  1321.7 2683.45
#Mann= 3 , 0 , 0
       0     .08       0   677.8    .045       0   692.8     .08       0
Bank Sta=677.8,692.8
XS Rating Curve= 0 ,0
Exp/Cntr=0.3,0.1

Type RM Length L Ch R = 1 ,25577.8 ,753.7,751.6,749
XS GIS Cut Line= 2
     2152118.432      405310.905     2150952.829      405106.557
#Sta/Elev= 30
       0 2706.11    50.1 2686.28   100.3 2664.39   130.4 2652.18   150.4 2642.85
   210.6 2608.21   250.7 2585.92   270.8  2572.9   300.9 2552.16   320.9 2540.04
     341 2529.54     351 2525.28   371.1 2519.04   391.1 2515.28   568.7 2501.36
   581.7 2501.08   583.7 2501.17     702 2508.86   802.3 2510.98   812.3 2512.24
   822.4 2514.99   882.5 2536.81   922.6 2552.37   962.8 2569.83   992.8 2584.06
  1012.9 2594.52    1033 2606.19  1083.1 2638.98  1103.2 2651.34  1183.4 2695.07
#Mann= 3 , 0 , 0
       0     .08       0   568.7    .045       0   583.7     .08       0
Bank Sta=568.7,583.7
XS Rating Curve= 0 ,0
Exp/Cntr=0.3,0.1

Type RM Length L Ch R = 1 ,24826.2 ,795.2,793.5,792.3
XS GIS Cut Line= 2
     2152346.584      404528.173     2150960.144      404467.254
#Sta/Elev= 30
       0 2648.29    70.4 2628.46     171 2604.63   191.1 2598.51   211.2 2591.42
   281.6 2563.69   301.7 2553.86   331.9 2535.29   341.9 2530.13   382.1 2511.93
   392.2  2508.2   402.2  2505.7   412.3 2504.19     543 2490.94   623.5 2487.06
   784.4 2483.19   794.4 2482.96   799.4  2483.2   834.7 2485.56   925.2 2487.02
   935.2  2488.3   945.3 2491.94   955.4 2497.67   975.5 2510.43  1025.8 2543.21
  1236.9  2687.5  1287.2    2721  1337.5 2751.99  1357.6 2763.34  1387.8 2778.93
#Mann= 3 , 0 , 0
       0     .08       0   784.4    .045       0   799.4     .06       0
Bank Sta=784.4,799.4
XS Rating Curve= 0 ,0
Exp/Cntr=0.3,0.1

Type RM Length L Ch R = 1 ,24032.7 ,254.5,261.6,268.1
XS GIS Cut Line= 2
     2152220.544      403750.927      2151010.56      403696.309
#Sta/Elev= 30
       0 2649.88    30.3 2632.02    70.6 2610.09   100.9 2594.88   131.2 2580.51
   161.5 2566.93   252.3 2527.94   333.1 2491.21   373.5 2474.33   383.6 2471.06
   393.6 2469.26   403.7 2468.72   484.5 2466.68   595.5 2467.86   635.9 2467.29
   706.5 2463.69   749.5 2460.25     757 2460.02   764.5 2460.28   777.2 2461.91
   787.3 2466.13   797.4 2473.54   837.8 2508.28   857.9 2523.71   938.7 2579.33
     969 2599.25   999.2 2618.32  1039.6 2642.46  1090.1 2671.22  1211.2 2737.32
#Mann= 3 , 0 , 0
       0     .08       0   749.5    .045       0   764.5     .06       0
Bank Sta=749.5,764.5
XS Rating Curve= 0 ,0
Exp/Cntr=0.3,0.1

Type RM Length L Ch R = 1 ,23771.1 ,325.2,326.6,327.9
XS GIS Cut Line= 3
     2152194.007      403522.535     2151713.612      403524.651
     2151076.612      403344.767
#Sta/Elev= 30
       0 2656.01      20 2642.89      60 2614.08   140.1 2559.69   160.1 2547.35
   210.2 2518.69   240.2 2500.22   260.2 2492.08   290.2 2486.13   350.3 2464.69
   360.3 2462.56   460.4 2457.87   580.7 2459.55   657.6 2455.73   660.9 2455.59
   672.6 2455.89   711.1  2459.5   721.1 2461.51   741.2 2468.94   771.2 2482.69
   781.3 2488.19   841.4 2525.64   891.6  2550.5   921.7 2566.46   951.8 2585.45
    1022 2632.76    1032 2637.74  1062.1 2649.98  1072.1 2655.45  1142.3 2698.78
#Mann= 3 , 0 , 0
       0      .1       0   657.6    .045       0   672.6      .1       0
#XS Ineff= 2 , 0
          580.95 2503.69
Permanent Ineff=
       F       F
Bank Sta=657.6,672.6
XS Rating Curve= 0 ,0
Exp/Cntr=0.3,0.1

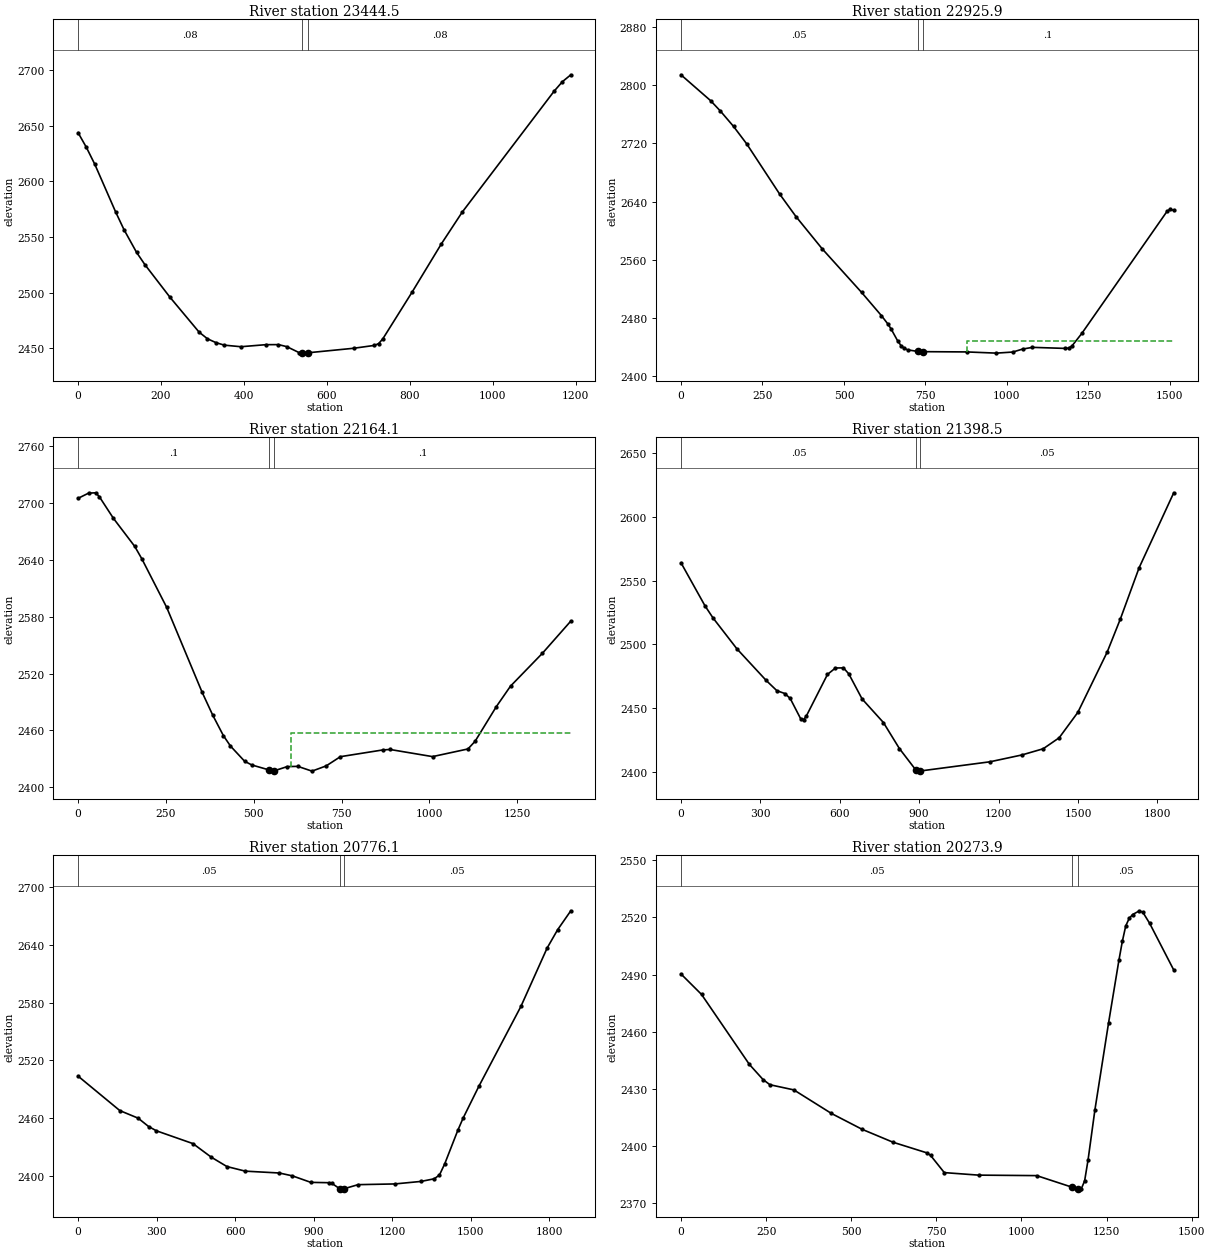
Type RM Length L Ch R = 1 ,23444.5 ,520,518.7,516.9
XS GIS Cut Line= 2
     2152201.638      403366.505     2151079.882       402973.68
#Sta/Elev= 30
       0 2643.88    20.1 2630.63    40.3  2615.5    90.6  2572.6   110.8 2556.63
     141 2536.26   161.2 2525.16   221.6 2495.87   292.1 2464.38   312.2 2458.43
   332.4 2455.02   352.5 2452.72   392.8 2451.29   453.3 2453.14   483.5 2453.19
   503.6 2451.36   533.8 2445.89   540.3 2445.66   543.9 2445.53   555.3 2445.87
   664.8  2449.9   715.1 2452.49   725.2 2454.13   735.3 2458.46   805.8 2500.41
   876.3 2543.77   926.7 2572.37  1148.3 2681.14  1168.4 2689.73  1188.6  2695.9
#Mann= 3 , 0 , 0
       0     .08       0   540.3    .045       0   555.3     .08       0
Bank Sta=540.3,555.3
XS Rating Curve= 0 ,0
Exp/Cntr=0.3,0.1

Type RM Length L Ch R = 1 ,22925.9 ,756.4,761.8,767.1
XS GIS Cut Line= 2
     2152641.494      402936.685     2151188.766      402518.419
#Sta/Elev= 30
       0 2814.47    90.7 2778.99   120.9 2764.62   161.2 2743.49   201.6 2719.46
   302.4 2650.56   352.7 2619.44   433.4 2574.92   554.3 2514.92   614.8 2483.14
   634.9 2471.48     645 2464.41   665.2 2447.97   675.2 2441.78   685.3 2437.94
   695.4 2435.94     726 2433.84     741 2433.48   876.8 2433.11   967.5 2431.46
  1017.9 2432.94  1048.1 2437.04  1078.4  2439.4  1179.2 2437.95  1189.2 2438.32
  1199.3 2441.22  1229.6 2458.49  1491.6 2626.82  1501.7 2629.55  1511.7 2627.81
#Mann= 3 , 0 , 0
       0     .05       0     726    .045       0     741      .1       0
#XS Ineff= 2 , 0
                          876.39         2448.64
Permanent Ineff=
       F       F
Bank Sta=726,741
XS Rating Curve= 0 ,0
Exp/Cntr=0.3,0.1

Type RM Length L Ch R = 1 ,22164.1 ,774.1,765.6,757
XS GIS Cut Line= 2
     2152570.538      402286.879     2151345.616      401603.462
#Sta/Elev= 30
       0 2705.03    30.3 2710.61    50.5 2710.87    60.6 2706.77   100.9 2683.81
   161.5 2654.21   181.6 2641.14   252.3 2589.88   353.2 2500.19   383.5 2475.96
   413.7 2454.44   433.9  2443.4   474.3  2427.3   494.5 2423.43   544.1 2418.13
   559.1 2417.33   595.4 2421.69   625.6 2421.94     666 2416.91   706.4 2422.44
   746.8 2432.17   867.8  2439.3     888 2439.78  1009.1 2432.24    1110 2440.33
  1130.2 2448.38  1190.8 2485.07  1231.1 2506.68  1321.9 2541.38  1402.7 2575.35
#Mann= 3 , 0 , 0
       0      .1       0   544.1    .045       0   559.1      .1       0
#XS Ineff= 2 , 0
                          604.83         2456.82
Permanent Ineff=
       F       F
Bank Sta=544.1,559.1
XS Rating Curve= 0 ,0
Exp/Cntr=0.3,0.1

Type RM Length L Ch R = 1 ,21398.5 ,625.1,622.4,619.6
XS GIS Cut Line= 2
     2153276.362       401461.55     2151435.244      401185.196
#Sta/Elev= 30
       0 2563.89    90.6 2530.25   120.8  2520.8   211.3 2496.58     322 2471.83
   362.3 2463.84   392.5 2461.61   412.6 2457.78   452.9 2441.59   462.9 2441.18
     473 2443.76   553.5 2476.56   583.7  2481.6   613.9 2481.68     634 2476.99
   684.3 2457.37   764.8 2438.94   825.2 2418.59   888.5 2401.48   895.6 2400.92
   903.5 2401.02  1167.4 2408.22  1288.1 2413.57  1368.6 2418.42    1429 2427.02
  1499.5 2446.89  1610.2 2493.98  1660.5 2520.13  1730.9 2559.96  1861.7  2618.6
#Mann= 3 , 0 , 0
       0     .05       0   888.5    .045       0   903.5     .05       0
Bank Sta=888.5,903.5
XS Rating Curve= 0 ,0
Exp/Cntr=0.3,0.1

Type RM Length L Ch R = 1 ,20776.1 ,488.1,502.3,516.2
XS GIS Cut Line= 3
     2153239.017      401218.807      2152787.14       400725.85
     2151573.422      400695.974
#Sta/Elev= 30
       0 2503.46   159.7 2467.56   229.6 2459.69   269.5 2451.02   299.4 2446.54
   439.2  2433.2     509  2419.1   568.9 2409.34   638.8 2404.56   769.1 2402.63
   819.2 2399.65   889.5 2392.88   959.7 2392.53   969.7 2391.89  1001.1 2386.03
  1009.9 2385.85  1016.1 2386.24  1070.1  2390.5  1210.6 2391.25  1310.9 2393.88
  1361.1  2396.6  1381.1 2400.58  1401.2 2412.23  1451.4 2447.22  1471.4 2459.75
  1531.6 2492.88  1692.2 2575.94  1792.5 2636.78  1832.6 2655.81  1882.8 2675.45
#Mann= 3 , 0 , 0
       0     .05       0  1001.1    .045       0  1016.1     .05       0
Bank Sta=1001.1,1016.1
XS Rating Curve= 0 ,0
Exp/Cntr=0.3,0.1

Type RM Length L Ch R = 1 ,20273.9 ,1035.4,1048.8,1062.1
XS GIS Cut Line= 3
     2153422.008      400938.718     2152645.228      400367.336
      2152260.42      400075.486
#Sta/Elev= 30
       0 2490.29    60.3 2479.58   200.9 2442.88   241.1 2434.94   261.2 2432.24
   331.5 2429.53     442 2417.17   532.4 2408.84   622.8  2402.1   723.2 2396.48
   733.3 2395.15   773.4 2386.18   873.9 2384.86  1044.8  2384.6  1148.7 2378.53
  1165.5 2377.52  1175.6 2377.59  1185.6 2381.84  1195.7 2392.82  1215.8 2419.04
  1256.1 2464.84  1286.3 2497.44  1296.3 2507.32  1306.4 2515.49  1316.5 2519.43
  1326.5 2521.44  1346.6 2523.39  1356.7 2522.62  1376.8 2516.77  1447.3  2492.4
#Mann= 3 , 0 , 0
       0     .05       0  1148.7    .045       0  1165.5     .05       0
Bank Sta=1148.7,1165.5
XS Rating Curve= 0 ,0
Exp/Cntr=0.3,0.1

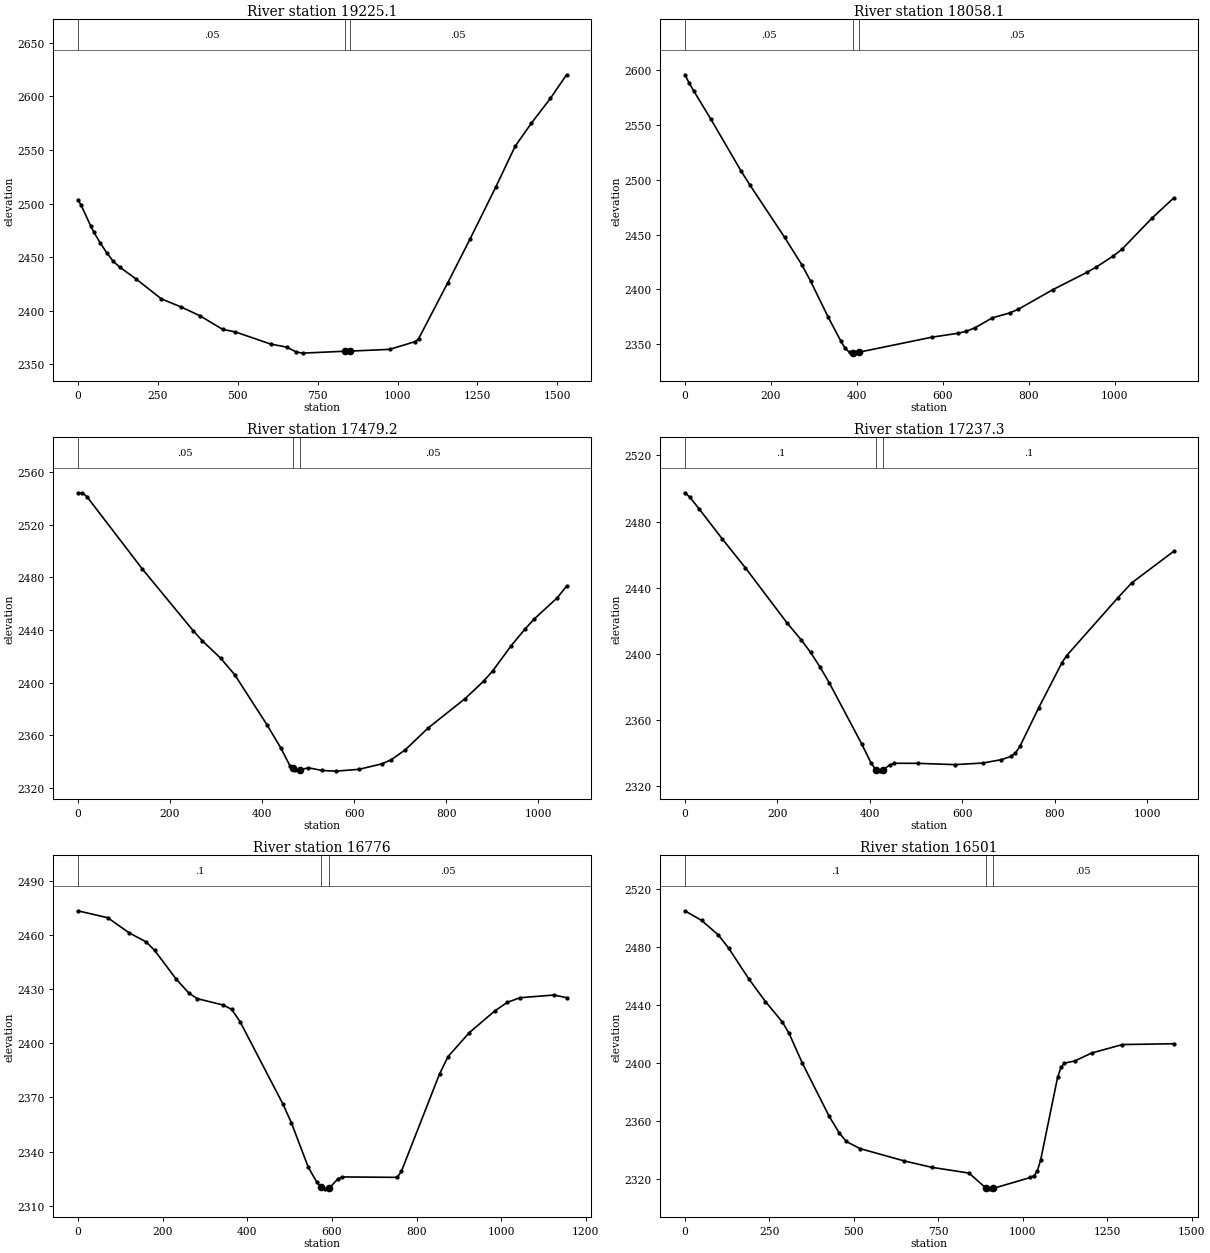
Type RM Length L Ch R = 1 ,19225.1 ,1169.1,1167,1164.4
XS GIS Cut Line= 2
     2153671.474       400518.25     2153158.363       399078.23
#Sta/Elev= 30
       0 2503.53    10.1 2498.59    40.2 2479.06    50.3 2473.16    70.4 2463.12
    90.5 2454.03   110.6  2446.2   130.7 2440.78     181 2429.94   261.5 2411.08
   321.8 2403.75   382.2 2395.34   452.6 2382.77   492.8  2380.3   603.4    2369
   653.7 2366.14   683.9 2361.55     704 2360.56     837 2362.37     852 2362.45
   975.6 2364.08    1056 2371.36  1066.1 2374.02  1156.6 2425.79    1227 2466.95
  1307.4 2515.34  1367.8 2553.24  1418.1 2574.61  1478.4 2598.03  1528.7 2619.96
#Mann= 3 , 0 , 0
       0     .05       0     837    .045       0     852     .05       0
Bank Sta=837,852
XS Rating Curve= 0 ,0
Exp/Cntr=0.3,0.1

Type RM Length L Ch R = 1 ,18058.1 ,581.4,578.9,576.4
XS GIS Cut Line= 3
     2154676.806      399818.362     2154452.735      399344.078
        2154027.      398903.405
#Sta/Elev= 30
       0 2595.71    10.1  2588.1    20.2 2581.26    60.5 2555.23   131.1 2507.75
   151.3 2495.22     232 2447.51   272.4 2422.28   292.5 2407.63   332.9 2375.21
   363.2 2352.71   373.2 2346.24   383.3 2342.59   390.7 2342.13   393.4 2341.96
   405.7 2342.86   574.8  2356.5     635 2360.03   655.1 2361.86   675.2 2365.08
   715.4 2374.11   755.6 2378.56   775.7 2381.89     856 2399.76   936.4 2415.76
   956.5 2420.24   996.7 2430.46  1016.8 2436.53  1087.1 2465.06  1137.3 2483.29
#Mann= 3 , 0 , 0
       0     .05       0   390.7    .045       0   405.7     .05       0
Bank Sta=390.7,405.7
XS Rating Curve= 0 ,0
Exp/Cntr=0.3,0.1

Type RM Length L Ch R = 1 ,17479.2 ,240.3,241.9,243.5
XS GIS Cut Line= 2
      2155151.09      399456.114     2154594.647       398552.36
#Sta/Elev= 30
       0 2544.11      10 2544.26      20 2541.22   140.2 2486.36   250.3 2439.64
   270.3  2431.9   310.4 2418.59   340.4 2406.26   410.5 2368.26   440.6 2350.65
   460.6 2337.02   466.5 2335.13   470.6 2333.82   481.5 2333.83   500.6 2335.47
   530.7 2333.41   560.7 2332.93   610.8 2334.31   660.8  2338.5   680.8 2341.63
   710.9 2349.05     761 2365.75     841 2387.97   881.1 2401.18   901.1 2409.07
   941.2  2428.2   971.2 2440.83   991.2 2448.44  1041.3  2464.6  1061.3 2473.35
#Mann= 3 , 0 , 0
       0     .05       0   466.5    .045       0   481.5     .05       0
Bank Sta=466.5,481.5
XS Rating Curve= 0 ,0
Exp/Cntr=0.3,0.1

Type RM Length L Ch R = 1 ,17237.3 ,467.5,461.3,455.1
XS GIS Cut Line= 2
     2155309.075      399309.879     2154821.125      398371.877
#Sta/Elev= 30
       0 2497.37    10.1 2494.89    30.2 2487.87    80.6 2469.58   130.9    2452
   221.5 2418.52   251.7 2408.42   271.9 2400.89     292 2392.18   312.2 2382.54
   382.6  2345.5   402.8 2333.94   412.9 2330.03   422.9 2329.09     429    2330
   443.1 2332.81   453.1 2333.84   503.5 2333.81     584 2333.02   644.5 2333.98
   684.8 2336.03   704.9 2337.94     715 2339.96     725 2344.16   765.3  2367.3
   815.6 2394.57   825.7 2398.85   936.5 2433.83   966.7 2442.93  1057.3 2461.94
#Mann= 3 , 0 , 0
       0      .1       0   412.9    .045       0     429      .1       0
Bank Sta=412.9,429
XS Rating Curve= 0 ,0
Exp/Cntr=0.3,0.1

Type RM Length L Ch R = 1 ,16776   ,283.3,275,266.3
XS GIS Cut Line= 3
     2155416.241      399246.981     2155565.622      398765.228
     2155121.214      398290.944
#Sta/Elev= 30
       0  2473.3    70.6 2469.49     121 2461.14   161.4  2456.1   181.6 2451.35
     232 2435.58   262.3 2427.75   282.4 2424.68     343 2421.19   363.2  2418.8
   383.3 2411.92   484.2 2366.48   504.4 2356.01   544.4 2331.38   564.4 2323.18
   574.4 2320.42   584.4 2319.29   594.4 2319.98   614.4    2325   624.4 2326.04
   754.4  2325.8   764.4 2329.22   854.4 2383.03   874.4 2392.62   924.4 2405.83
   984.4  2417.8  1014.4 2422.65  1044.4 2425.21  1124.3  2426.7  1154.3 2425.25
#Mann= 3 , 0 , 0
       0      .1       0   574.4    .045       0   594.4     .05       0
Bank Sta=574.4,594.4
XS Rating Curve= 0 ,0
Exp/Cntr=0.3,0.1

Type RM Length L Ch R = 1 ,16501   ,696.7,701.9,706.9
XS GIS Cut Line= 3
     2156368.543      399007.972     2156089.938      398684.086
     2155168.764       398247.74
#Sta/Elev= 30
       0 2504.82    49.7 2498.16    99.4 2488.05   129.2 2479.18   188.8 2457.99
   238.4 2442.28   288.1 2428.28     308 2420.47   347.7 2399.76   427.2 2363.09
   457.5 2351.46   477.7 2345.84     518 2340.94   649.2  2332.4     730 2328.03
     841 2324.02   891.5  2313.6   901.6 2312.97   911.6 2313.41  1022.7    2321
  1032.8 2322.02  1042.8 2325.29  1052.9 2332.92  1103.4 2390.24  1113.5 2397.09
  1123.6 2399.83  1153.8  2401.3  1204.3 2406.81  1295.1 2412.64  1446.5 2413.19
#Mann= 3 , 0 , 0
       0      .1       0   891.5    .045       0   911.6     .05       0
Bank Sta=891.5,911.6
XS Rating Curve= 0 ,0
Exp/Cntr=0.3,0.1

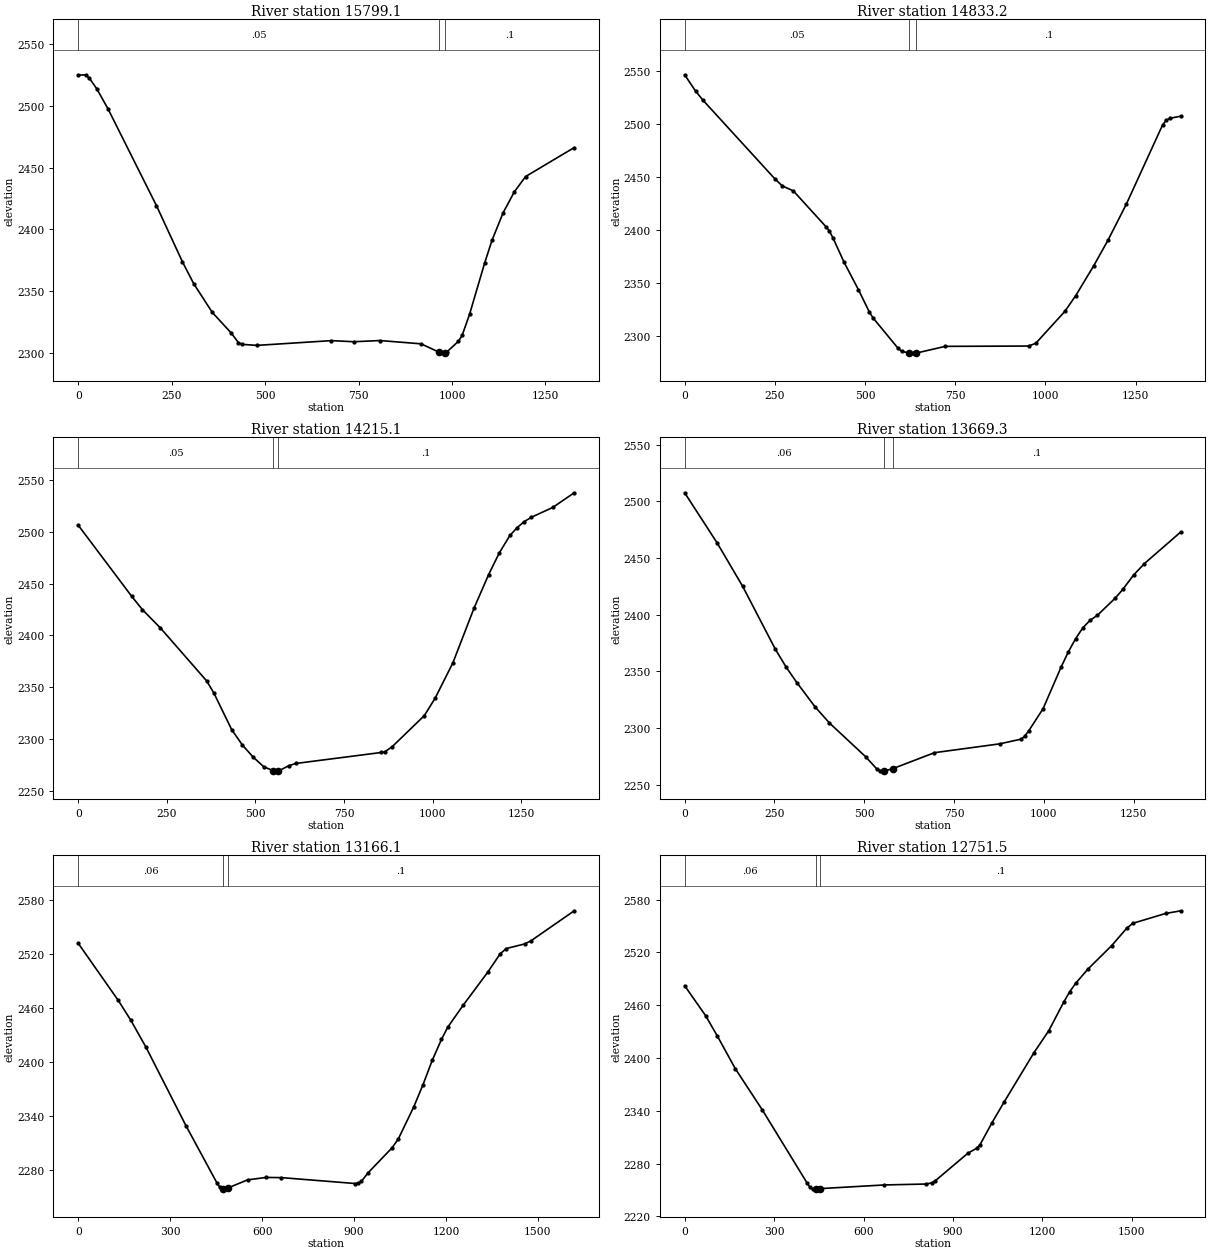
Type RM Length L Ch R = 1 ,15799.1 ,984.9,965.9,946.9
XS GIS Cut Line= 3
     2156947.394      397939.899     2156252.773      398074.342
     2155767.286      397689.687
#Sta/Elev= 30
       0 2524.99    19.9 2525.25    29.9 2522.49    49.8 2513.89    79.7  2497.7
   209.3 2419.28     279 2373.62   308.9 2356.06   358.7 2332.73   408.6 2316.31
   428.5 2308.31   438.5 2306.81   478.3    2306   677.6 2309.85   737.5 2308.95
   807.4 2309.92   917.3 2307.26   965.3 2300.51   977.2 2299.72   980.3  2300.1
   987.2 2300.94  1017.2 2309.29  1027.2 2314.06  1047.2 2331.34  1087.1  2372.4
  1107.1 2391.16  1137.1  2413.6  1167.1 2430.56    1197 2442.82  1326.9 2466.28
#Mann= 3 , 0 , 0
       0     .05       0   965.3    .045       0   980.3      .1       0
Bank Sta=965.3,980.3
XS Rating Curve= 0 ,0
Exp/Cntr=0.3,0.1

Type RM Length L Ch R = 1 ,14833.2 ,624.4,618.1,611.6
XS GIS Cut Line= 2
      2156932.64       396897.38     2155579.925      397141.217
#Sta/Elev= 30
       0 2546.46    30.1 2531.21    50.2 2522.73   250.8 2448.07   270.9 2441.63
     301  2437.1   391.3 2403.37   401.3 2398.99   411.4 2392.38   441.4 2370.01
   481.6 2343.85   511.7  2322.9   521.7 2317.41   591.9 2288.44     602 2285.68
     622 2284.29   632.1 2284.07   642.1 2284.15   722.4 2290.45   953.1 2290.75
   973.2 2293.39  1053.5 2323.36  1083.6 2338.17  1133.7 2366.44  1173.9    2391
    1224  2424.5  1324.4 2499.13  1334.4 2503.64  1344.4 2505.45  1374.5 2507.45
#Mann= 3 , 0 , 0
       0     .05       0     622    .045       0   642.1      .1       0
Bank Sta=622,642.1
XS Rating Curve= 0 ,0
Exp/Cntr=0.3,0.1

Type RM Length L Ch R = 1 ,14215.1 ,543.9,545.8,547.8
XS GIS Cut Line= 2
     2156483.759      396242.317     2155228.961      396862.247
#Sta/Elev= 30
       0 2506.37     151 2437.72   181.2 2424.88   231.6 2407.35   362.5 2356.11
   382.6 2344.57     433 2309.19   463.2 2294.29   493.4  2282.7   523.6 2273.26
   550.1 2269.46   563.9 2269.05   565.1 2269.17   594.1 2274.24   614.2 2276.45
   855.9 2287.08   865.9  2287.8   886.1 2292.66   976.7 2322.59  1006.9 2339.22
  1057.2 2373.42  1117.6 2426.79  1157.9 2458.46  1188.1  2479.5  1218.3 2496.47
  1238.5 2503.99  1258.6 2509.84  1278.8 2514.02  1339.2 2523.53  1399.6 2537.63
#Mann= 3 , 0 , 0
       0     .05       0   550.1    .045       0   565.1      .1       0
Bank Sta=550.1,565.1
XS Rating Curve= 0 ,0
Exp/Cntr=0.3,0.1

Type RM Length L Ch R = 1 ,13669.3 ,499.7,503.2,506.3
XS GIS Cut Line= 2
     2156162.973      395870.078     2154874.564      396366.769
#Sta/Elev= 30
       0 2507.52    90.7 2463.18   161.3 2425.15     252 2369.87   282.2 2353.96
   312.4 2340.17   362.8 2318.87   403.2 2304.51     504 2274.74   534.2 2264.27
   544.3 2262.41   554.4  2262.1   579.1 2264.24   695.5 2278.37   876.9 2286.15
   937.4 2290.36   947.4 2293.19   957.5 2297.44   997.8 2317.12  1048.2 2353.96
  1068.4 2367.38  1088.5 2378.89  1108.7 2388.58  1128.9 2395.11    1149 2399.49
  1199.4 2414.86  1219.6 2422.27  1249.8    2435    1280 2445.12  1380.8 2472.88
#Mann= 3 , 0 , 0
       0     .06       0   554.4    .045       0   579.1      .1       0
Bank Sta=554.4,579.1
XS Rating Curve= 0 ,0
Exp/Cntr=0.3,0.1

Type RM Length L Ch R = 1 ,13166.1 ,416.9,414.6,412.3
XS GIS Cut Line= 3
     2156034.891       395484.63     2154907.067      395734.843
     2154660.589      396126.967
#Sta/Elev= 30
       0 2531.43   130.6    2468   170.8 2446.45     221 2416.09   351.6 2328.82
     452 2265.66   462.1 2260.44   472.1 2258.35   487.9 2259.54   552.5 2268.61
   612.8 2271.32     663 2271.14   904.1 2264.57   914.2  2264.7   924.2 2266.91
   944.3 2275.87  1024.6 2304.41  1044.7 2314.16    1095 2349.73  1125.1 2374.31
  1155.2 2401.34  1185.4 2424.61  1205.6 2438.06  1255.9 2462.49  1336.5 2499.32
  1376.8 2519.64  1396.9 2525.58  1457.3 2530.74  1477.4 2534.14  1618.4 2567.48
#Mann= 3 , 0 , 0
       0     .06       0   472.1    .045       0   487.9      .1       0
Bank Sta=472.1,487.9
XS Rating Curve= 0 ,0
Exp/Cntr=0.3,0.1

Type RM Length L Ch R = 1 ,12751.5 ,427.6,445.2,461.9
XS GIS Cut Line= 3
     2155912.459      395044.781     2155192.376      395286.388
     2154306.485      395466.409
#Sta/Elev= 30
       0 2482.06      70 2448.18   109.9 2424.76   169.9 2387.82   259.8 2341.36
   409.8 2258.46   419.7 2253.49   429.7 2251.16   439.7 2251.08   455.4 2251.68
   669.6 2255.83   809.8 2256.87   829.8 2258.25   839.9 2260.36   950.4    2292
   980.5 2297.67   990.6 2301.45  1030.7 2326.47  1070.9 2349.68  1171.4 2405.94
  1221.6  2431.2  1271.8 2463.72  1291.9 2475.49    1312 2485.04  1352.2 2500.83
  1432.5 2527.72  1482.7 2547.36  1502.8 2552.92  1613.3 2564.17  1663.5 2567.15
#Mann= 3 , 0 , 0
       0     .06       0   439.7    .045       0   455.4      .1       0
Bank Sta=439.7,455.4
XS Rating Curve= 0 ,0
Exp/Cntr=0.3,0.1

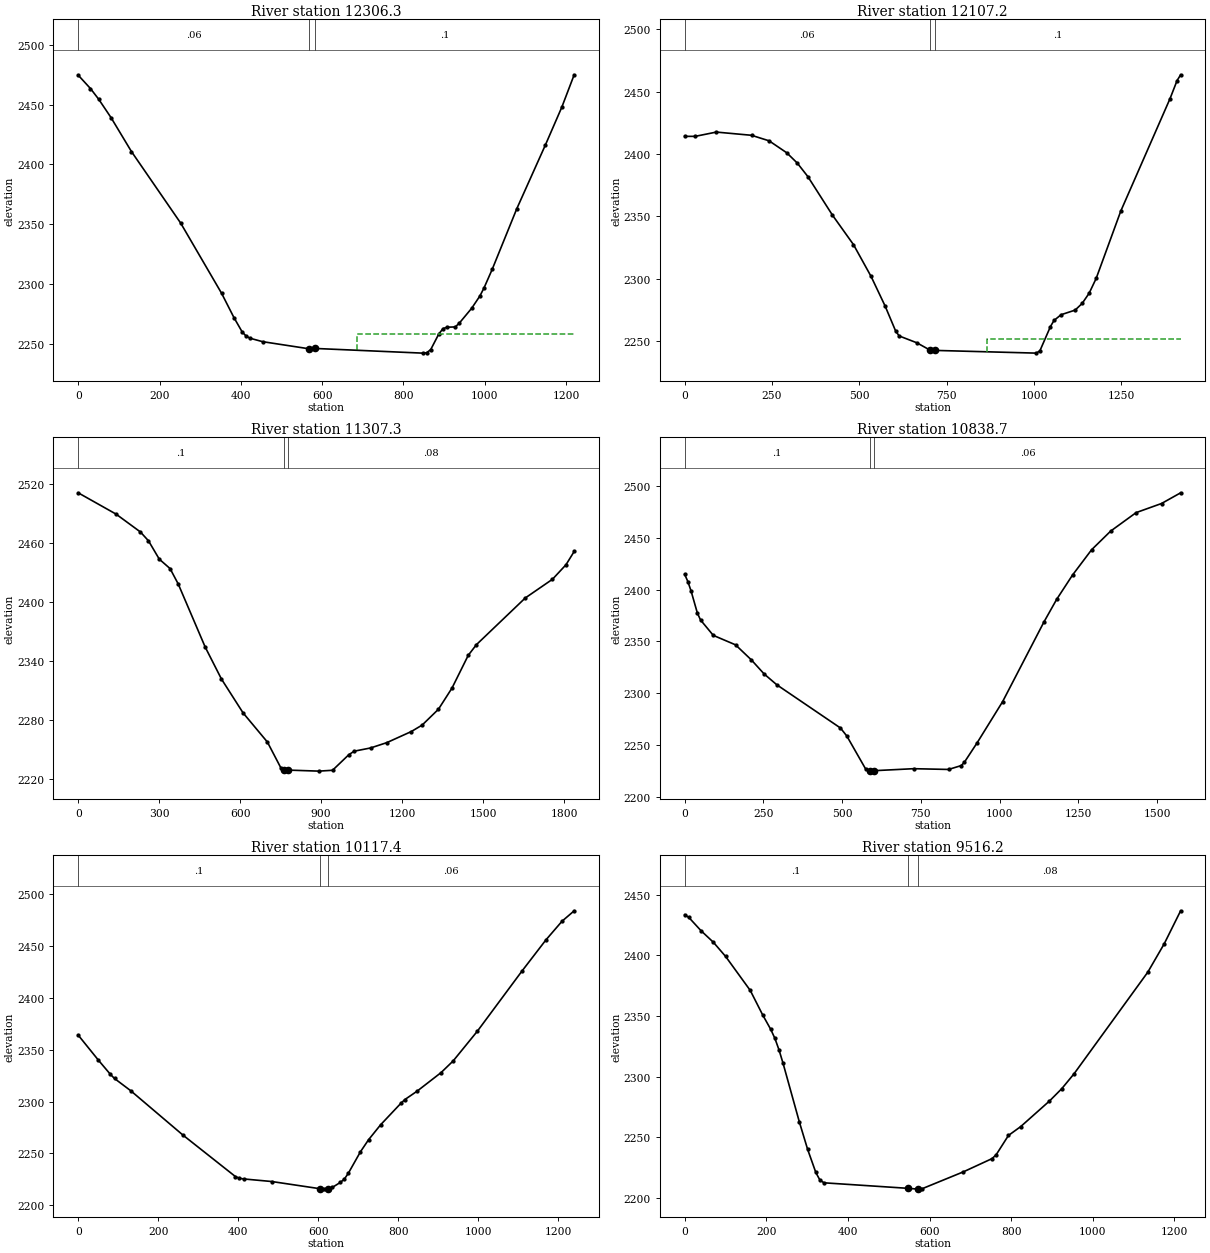
Type RM Length L Ch R = 1 ,12306.3 ,198.3,199.1,199.8
XS GIS Cut Line= 2
     2155894.598      395009.174     2154786.922      394498.505
#Sta/Elev= 30
       0 2474.64    30.2 2463.45    50.4 2454.53    80.6 2439.24     131 2410.77
     252 2351.01   352.8 2292.22     383 2272.03   403.2 2260.06   413.3 2256.43
   423.4 2254.69   453.6 2251.89   568.3 2245.92   583.3 2246.22   846.8 2242.32
   856.8 2242.59   866.9 2245.27   887.1 2258.48   897.2  2262.8   907.2 2263.99
   927.4 2264.22   937.5 2267.49   967.7 2279.83   987.9 2290.09     998 2296.79
  1018.1 2312.31  1078.6 2363.01  1149.2 2416.48  1189.5 2448.03  1219.7 2474.94
#Mann= 3 , 0 , 0
       0     .06       0   568.3    .045       0   583.3      .1       0
#XS Ineff= 2 , 0
                           686.1         2258.23
Permanent Ineff=
       F       F
Bank Sta=568.3,583.3
XS Rating Curve= 0 ,0
Exp/Cntr=0.3,0.1

Type RM Length L Ch R = 1 ,12107.2 ,808.4,799.8,791
XS GIS Cut Line= 2
     2156114.703      394923.039     2154845.083      394288.229
#Sta/Elev= 30
       0 2414.18    30.2 2414.19    90.6 2417.62   191.3 2415.04   241.6  2410.6
     292 2401.03   322.2 2392.78   352.4 2381.96   422.8 2351.02   483.2 2327.27
   533.6 2301.71   573.8 2277.93     604 2257.82   614.1 2253.96   664.4 2248.51
   702.2 2242.62   717.2 2242.38  1006.7  2240.2  1016.8  2242.1    1047 2261.57
  1057.1 2266.41  1077.2 2271.01  1117.5 2274.72  1137.6 2280.07  1157.7  2288.3
  1177.9 2300.24  1248.3 2354.27  1389.3 2444.54  1409.4    2459  1419.5 2463.57
#Mann= 3 , 0 , 0
       0     .06       0   702.2    .045       0   717.2      .1       0
#XS Ineff= 2 , 0
                          866.33         2251.64
Permanent Ineff=
       F       F
Bank Sta=702.2,717.2
XS Rating Curve= 0 ,0
Exp/Cntr=0.3,0.1

Type RM Length L Ch R = 1 ,11307.3 ,469.3,468.7,468
XS GIS Cut Line= 3
     2156514.189      394149.363     2155860.649      393925.292
     2154717.886      393831.929
#Sta/Elev= 30
       0  2510.6   140.2 2488.98   230.3 2470.87   260.3 2461.86   300.4 2443.21
   340.4  2433.6   370.5 2418.02   470.6 2353.82   530.7 2321.42   610.8 2287.02
   700.9  2257.4   751.2 2230.97   763.4 2229.09   778.4 2228.88     892 2227.84
   942.3  2228.7  1002.7 2244.55  1022.8 2248.12  1083.1 2251.37  1143.5  2256.8
    1234 2268.04  1274.2 2274.61  1334.6 2290.69  1384.9 2312.22  1445.2 2345.55
  1475.4 2356.33  1656.4 2403.77    1757 2422.74  1807.3 2437.54  1837.5 2450.99
#Mann= 3 , 0 , 0
       0      .1       0   763.4    .045       0   778.4     .08       0
Bank Sta=763.4,778.4
XS Rating Curve= 0 ,0
Exp/Cntr=0.3,0.1

Type RM Length L Ch R = 1 ,10838.7 ,725.4,721.3,717
XS GIS Cut Line= 2
     2156499.251      393499.557     2154927.019      393417.398
#Sta/Elev= 30
       0 2414.68    10.1 2407.76    20.2 2398.75    40.4 2377.23    50.5 2370.62
    90.8 2355.83   161.5 2346.69   211.9  2332.1   252.3 2318.57   292.7 2308.09
   494.5 2266.45   514.7 2258.72   575.2 2226.51   585.4 2224.83   586.8 2224.85
   601.8 2225.26   726.6 2227.18   837.6 2226.45     878 2230.19   888.1 2233.48
   928.5  2252.2  1009.2 2291.82  1140.4 2368.69  1180.8 2390.53  1231.2 2414.01
  1291.8 2438.44  1352.4 2456.46  1433.1 2474.27  1513.8 2483.07  1574.4 2493.37
#Mann= 3 , 0 , 0
       0      .1       0   586.8    .045       0   601.8     .06       0
Bank Sta=586.8,601.8
XS Rating Curve= 0 ,0
Exp/Cntr=0.3,0.1

Type RM Length L Ch R = 1 ,10117.4 ,598.9,601.2,603.5
XS GIS Cut Line= 2
     2156308.791      392786.264     2155083.869      392976.724
#Sta/Elev= 30
       0 2363.99    50.4  2339.9    80.6 2326.13    90.7 2322.21     131  2310.5
     262  2267.6   393.1 2227.65   403.1 2226.02   413.2 2225.42   483.8 2222.92
   604.7 2215.96   614.8 2215.59   624.9 2215.82   634.9 2217.18   655.1 2222.04
   665.2 2225.26   675.2 2230.91   705.5 2251.61   725.6 2263.13   755.9 2277.62
   806.3 2298.21   816.4  2301.9   846.6 2309.87     907  2327.9   937.3 2339.18
   997.8 2367.85  1108.6 2425.45  1169.1 2455.79  1209.4  2473.8  1239.6 2483.79
#Mann= 3 , 0 , 0
       0      .1       0   604.7    .045       0   624.9     .06       0
Bank Sta=604.7,624.9
XS Rating Curve= 0 ,0
Exp/Cntr=0.3,0.1

Type RM Length L Ch R = 1 ,9516.2  ,615.4,629.6,643.7
XS GIS Cut Line= 2
     2156107.127      392274.635     2154893.408      392338.122
#Sta/Elev= 30
       0 2433.63      10 2431.49    40.2 2420.41    70.3 2410.92   100.4 2399.16
   160.7 2371.12   190.8 2351.11   210.9 2338.95     221 2331.59     231 2322.19
   241.1 2310.94   281.2 2262.28   301.3 2239.85   321.4 2220.73   331.5 2214.41
   341.5 2212.21   546.9 2207.66   572.5 2206.99   582.6 2207.42     683 2221.27
   753.3  2232.2   763.4  2235.4   793.5 2251.34   823.6 2258.68     894 2279.77
   924.1 2289.96   954.2 2302.25    1135 2386.23  1175.2 2409.64  1215.4 2436.88
#Mann= 3 , 0 , 0
       0      .1       0   546.9    .045       0   572.5     .08       0
Bank Sta=546.9,572.5
XS Rating Curve= 0 ,0
Exp/Cntr=0.3,0.1