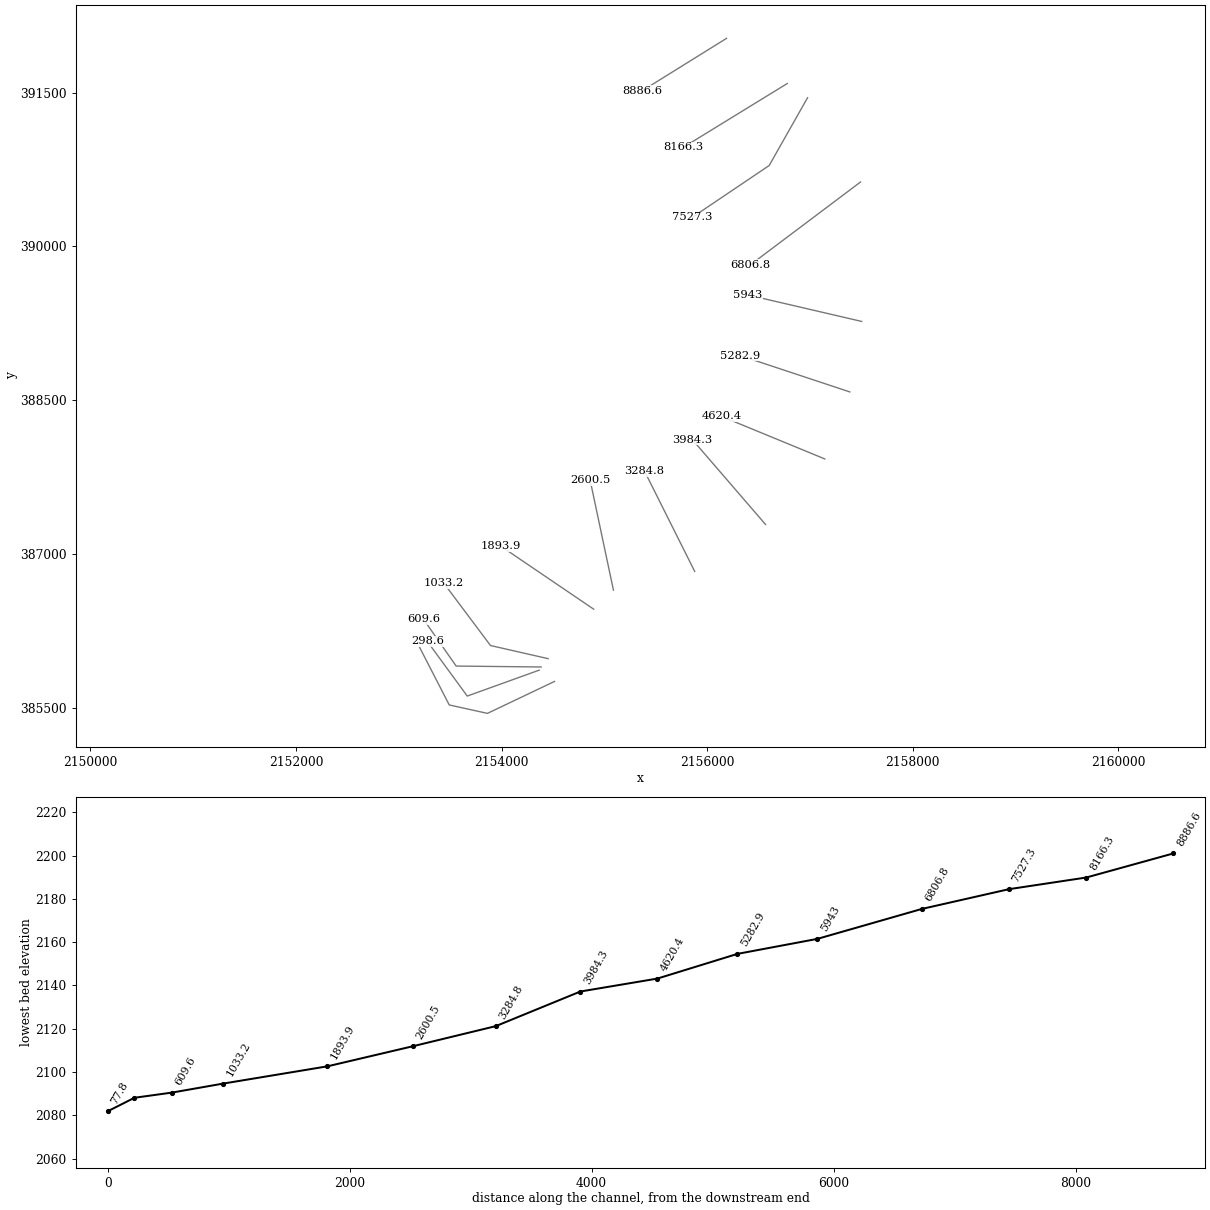
HEC-RAS study RobbinsRun.prj: RobbinsRun

--- RobbinsRun.g01 (geometry) --- (continued)

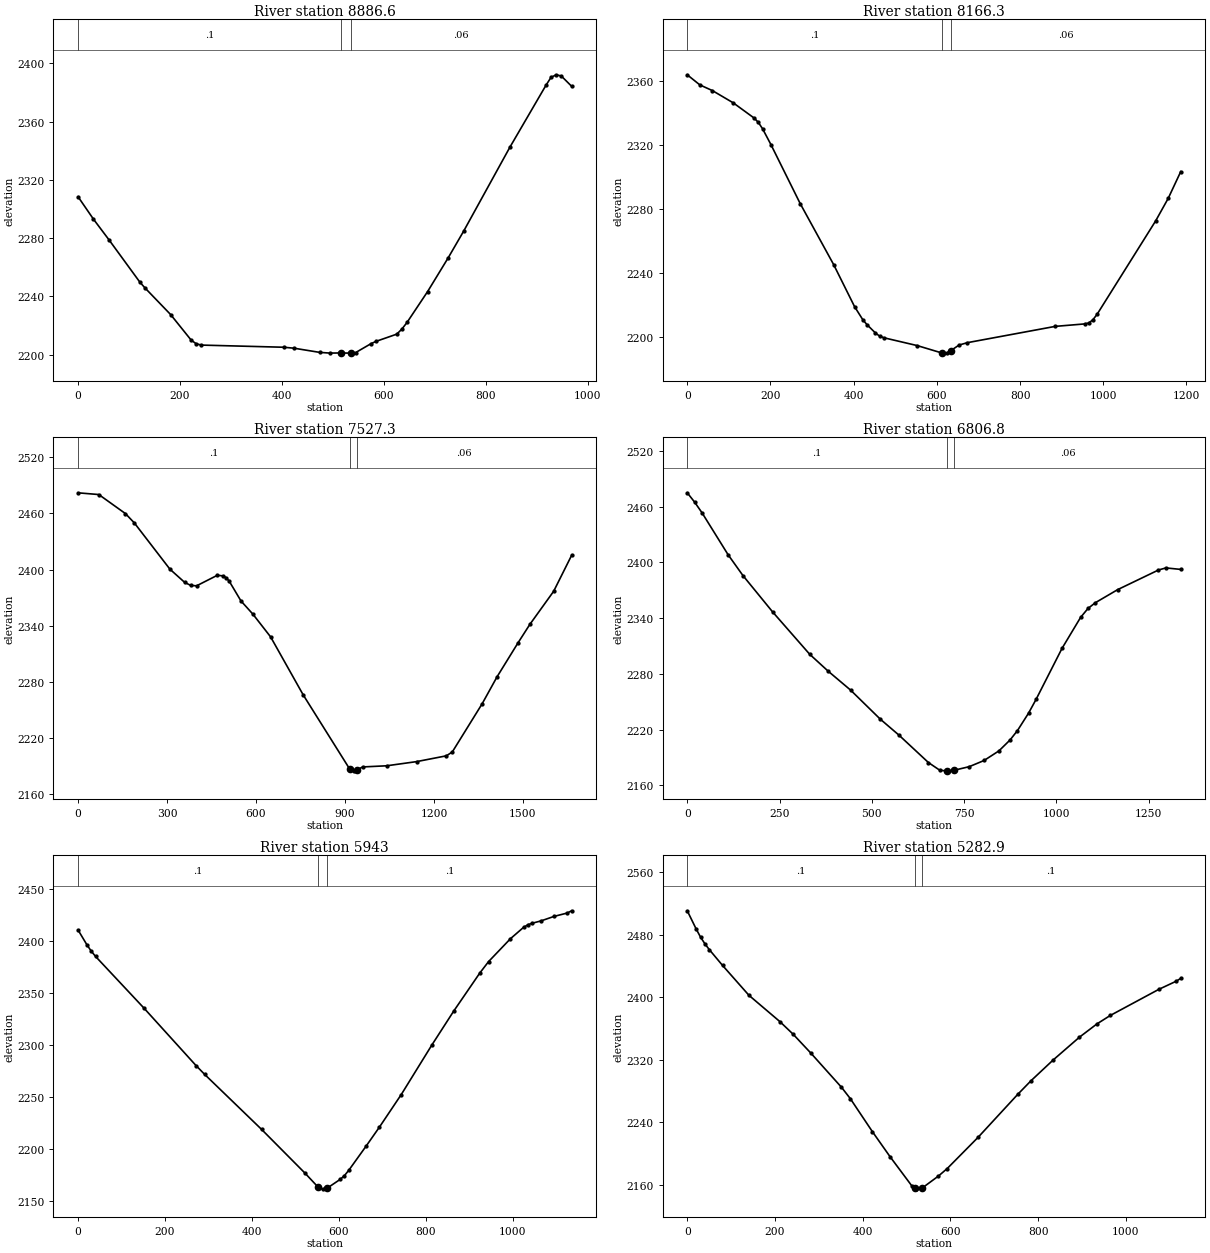
Type RM Length L Ch R = 1 ,8886.6  ,720.1,720.3,719.9
XS GIS Cut Line= 2
     2156189.286      392028.157     2155367.692      391516.528
#Sta/Elev= 30
       0 2308.33    30.2 2292.94    60.5 2278.83     121 2249.79   131.1 2245.78
   181.5 2227.46   221.8  2209.9   231.9 2207.35     242 2206.49   403.3 2205.01
   423.4 2204.36   473.9 2201.48     494    2201   514.9 2201.09   534.4 2200.97
   544.4 2201.34   574.7  2207.5   584.8  2209.1   625.1 2214.01   635.2 2217.52
   645.2 2222.04   685.6 2243.26   725.9  2266.4   756.2 2284.69   846.9 2342.34
   917.5 2384.77   927.6 2390.33   937.6 2392.08   947.7  2391.3   967.9 2384.27
#Mann= 3 , 0 , 0
       0      .1       0   514.9    .045       0   534.4     .06       0
Bank Sta=514.9,534.4
XS Rating Curve= 0 ,0
Exp/Cntr=0.3,0.1

Type RM Length L Ch R = 1 ,8166.3  ,638.5,639,640
XS GIS Cut Line= 2
      2156779.34      391587.484     2155768.937      390966.039
#Sta/Elev= 30
       0 2364.08    30.2 2357.77    60.3 2354.22   110.6 2346.52   160.8 2336.99
   170.9 2334.26     181  2330.3     201 2320.44   271.4 2283.48   351.8 2245.29
   402.1 2218.95   422.2 2210.65   432.3 2207.58   452.4 2202.43   462.4 2200.47
   472.5 2199.46   552.9 2194.55   613.2 2189.84   623.3 2189.92   633.3 2191.38
   653.4 2194.91   673.5  2196.4   884.6 2206.59     955 2208.12   965.1 2208.72
   975.1 2210.73   985.2 2214.18  1125.9 2272.63  1156.1 2286.76  1186.2 2303.48
#Mann= 3 , 0 , 0
       0      .1       0   613.2    .045       0   633.3     .06       0
Bank Sta=613.2,633.3
XS Rating Curve= 0 ,0
Exp/Cntr=0.3,0.1

Type RM Length L Ch R = 1 ,7527.3  ,719,720.5,721.9
XS GIS Cut Line= 3
      2156977.27      391449.306     2156603.818      390788.297
     2155853.872      390281.727
#Sta/Elev= 30
       0 2482.09    69.9 2480.25   159.8 2459.85   189.8 2449.86   309.7 2400.43
   359.6 2386.27   379.6 2383.14   399.6 2382.63   469.5 2393.89   489.5 2393.26
   499.5 2391.21   509.5  2387.7   549.4 2366.43   589.4 2352.39   649.3 2328.02
   759.2 2265.99   916.8 2186.27   930.2 2184.46   940.2 2185.93   960.3 2188.95
  1040.8 2190.17  1141.3 2194.62  1241.9 2200.82    1262 2204.95  1362.6 2256.44
  1412.8 2285.24  1483.2 2321.41  1523.4  2341.3  1603.9 2376.82  1664.2 2415.08
#Mann= 3 , 0 , 0
       0      .1       0   916.8    .045       0   940.2     .06       0
Bank Sta=916.8,940.2
XS Rating Curve= 0 ,0
Exp/Cntr=0.3,0.1

Type RM Length L Ch R = 1 ,6806.8  ,883.2,863.9,843.9
XS GIS Cut Line= 2
     2157492.633      390627.712     2156424.816      389823.179
#Sta/Elev= 30
       0 2475.03    20.1 2464.91    40.2 2453.37   110.6 2408.36   150.8 2385.94
   231.2  2346.8   331.7 2301.16     382 2282.87   442.3 2262.65   522.7 2231.38
     573 2214.28   653.4 2184.56   683.6 2176.43   703.7 2175.33   723.8 2176.35
     764 2180.14   804.2  2186.8   844.4 2197.13   874.6 2208.91   894.7 2219.06
   924.8 2237.85   944.9  2252.5  1015.3 2307.51  1065.6 2340.84  1085.7 2350.52
  1105.8 2356.74  1166.1 2370.78  1276.7 2391.93  1296.8 2394.16    1337 2392.56
#Mann= 3 , 0 , 0
       0      .1       0   703.7    .045       0   723.8     .06       0
Bank Sta=703.7,723.8
XS Rating Curve= 0 ,0
Exp/Cntr=0.3,0.1

Type RM Length L Ch R = 1 ,5943    ,662.2,660.1,658.1
XS GIS Cut Line= 2
     2157503.837      389268.348     2156398.419      389526.029
#Sta/Elev= 30
       0 2410.52    20.1 2396.48    30.1 2390.36    40.2 2385.17   150.7 2335.86
   271.2 2280.31   291.3 2271.71   421.9 2218.98   522.3  2176.7   552.5 2163.22
   562.5  2161.5   573.2 2162.51   602.7 2170.83   612.7 2174.51   622.8 2179.72
     663 2203.14   693.1 2221.12   743.3  2252.4   813.6 2299.96   863.8 2332.52
   924.1  2369.3   944.2 2380.23   994.4 2402.18  1024.6 2413.11  1034.6 2415.62
  1044.6  2417.1  1064.7 2419.32  1094.9 2423.68    1125 2426.88    1135 2429.01
#Mann= 3 , 0 , 0
       0      .1       0   552.5    .045       0   573.2      .1       0
Bank Sta=552.5,573.2
XS Rating Curve= 0 ,0
Exp/Cntr=0.3,0.1

Type RM Length L Ch R = 1 ,5282.9  ,664,662.4,660.9
XS GIS Cut Line= 2
     2157388.067      388581.196     2156319.995      388935.975
#Sta/Elev= 30
       0 2510.37    20.1 2487.32    30.2 2476.81    40.2 2468.19    50.2  2460.8
    80.4 2440.59   140.7 2402.32     211 2368.84   241.2 2352.75   281.4 2328.74
   351.7 2284.78   371.8 2270.29     422  2228.2   462.2 2196.23   512.5 2158.43
   519.8 2155.62   522.5 2154.58   534.8  2155.6   572.8  2171.3   592.9 2180.94
   663.2  2220.8   753.6  2275.7   783.8 2293.09     834 2319.46   894.3  2348.8
   934.5 2365.89   964.7 2376.59  1075.2 2409.92  1115.4 2420.48  1125.4 2424.07
#Mann= 3 , 0 , 0
       0      .1       0   519.8    .045       0   534.8      .1       0
Bank Sta=519.8,534.8
XS Rating Curve= 0 ,0
Exp/Cntr=0.3,0.1

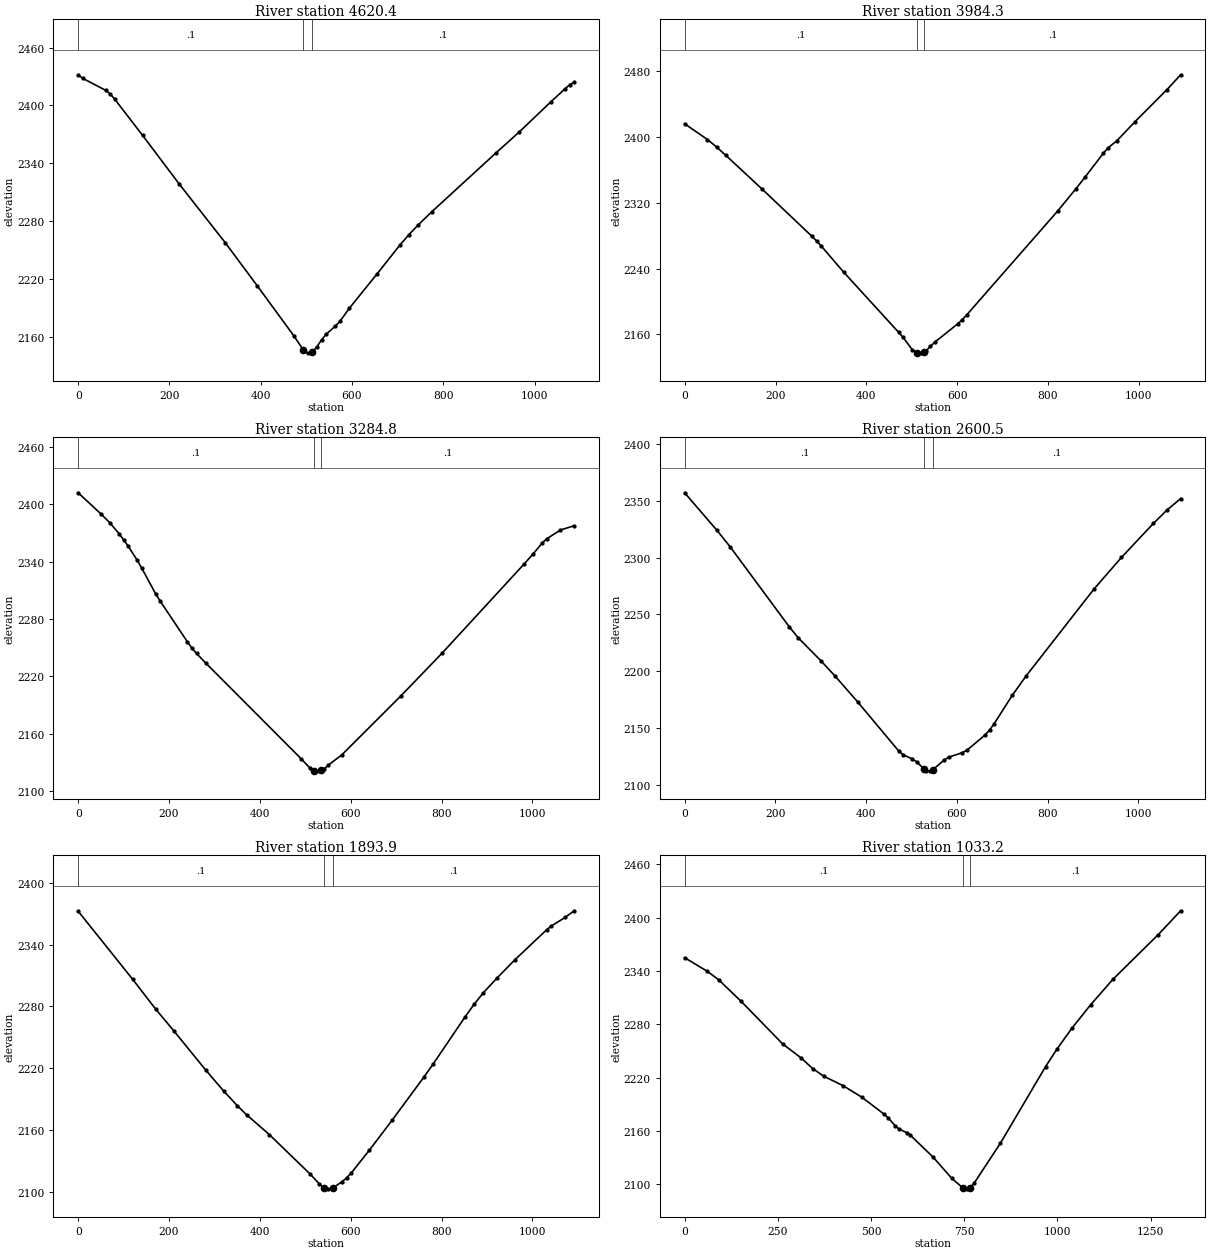
Type RM Length L Ch R = 1 ,4620.4  ,646.7,636.1,625.6
XS GIS Cut Line= 2
     2157145.323      387927.655     2156140.738      388342.187
#Sta/Elev= 30
       0 2431.71    10.1 2428.01    60.4 2415.58    70.4 2411.71    80.5  2406.2
   140.9 2369.05   221.4 2318.48     322 2257.79   392.4 2212.96   472.9 2160.88
   493.1  2146.6   503.1 2143.17     513 2144.17   523.2 2149.79   533.3 2156.98
   543.4 2162.78   563.5 2171.16   573.6 2176.16   593.7 2189.46   654.1 2224.83
   704.4 2254.86   724.5 2265.94   744.6  2275.9   774.8 2289.71   915.7 2350.85
     966 2372.24  1036.4    2404  1066.6 2417.11  1076.7 2421.34  1086.8 2423.98
#Mann= 3 , 0 , 0
       0      .1       0   493.1    .045       0     513      .1       0
Bank Sta=493.1,513
XS Rating Curve= 0 ,0
Exp/Cntr=0.3,0.1

Type RM Length L Ch R = 1 ,3984.3  ,705,699.5,693.9
XS GIS Cut Line= 2
      2156568.52      387288.912     2155856.105      388116.518
#Sta/Elev= 30
       0 2416.35    50.1 2397.18    70.1 2388.15    90.2 2378.11   170.3 2336.96
   280.5 2279.22   290.5  2273.7   300.6 2267.66   350.6 2235.42   470.9 2162.63
   480.9 2156.34   500.9 2141.56   510.9 2137.55     521  2137.2     527 2138.72
     531 2139.74     541 2145.49     551 2150.64   601.1 2172.84   611.1 2177.88
   621.1 2183.78   821.5 2310.31   861.6 2337.36   881.6 2351.46   921.7 2380.38
   931.7 2386.86   951.7 2395.72   991.8 2419.02    1062    2458    1092 2475.94
#Mann= 3 , 0 , 0
       0      .1       0   510.9    .045       0     527      .1       0
Bank Sta=510.9,527
XS Rating Curve= 0 ,0
Exp/Cntr=0.3,0.1

Type RM Length L Ch R = 1 ,3284.8  ,690.1,684.4,678.6
XS GIS Cut Line= 2
     2155878.994      386831.844     2155391.066      387808.892
#Sta/Elev= 30
       0 2411.74    50.1 2389.69    70.1 2380.18    90.2 2368.96   100.2 2362.58
   110.2 2355.96   130.2 2341.14   140.3 2332.78   170.3 2306.45   180.4 2298.79
   240.5 2256.17   250.5 2249.51   260.5 2244.04   280.5 2234.23     491 2134.08
     511 2124.04   520.1 2121.56     531 2121.21   535.1 2122.08     541 2123.34
   551.1 2127.59   581.1 2138.45   711.4 2200.16   801.6 2244.52   981.9 2337.41
  1001.9 2348.04    1022 2359.51    1032 2363.84    1062 2372.95  1092.1 2377.38
#Mann= 3 , 0 , 0
       0      .1       0   520.1    .045       0   535.1      .1       0
Bank Sta=520.1,535.1
XS Rating Curve= 0 ,0
Exp/Cntr=0.3,0.1

Type RM Length L Ch R = 1 ,2600.5  ,689,706.6,723.8
XS GIS Cut Line= 2
     2155088.514      386649.134     2154862.505      387718.451
#Sta/Elev= 30
       0 2357.19    70.2 2324.56   100.3 2309.59   230.6 2239.06   250.7 2229.21
   300.8 2208.94   330.9 2195.93     381 2173.04   471.3 2129.85   481.3 2126.35
   501.4 2122.72   511.4 2120.05     528 2113.57   531.4 2112.39   541.5 2111.94
  546.53 2113.14   571.5 2121.53   581.6 2124.18   611.6 2128.19   621.7 2130.23
   661.8 2143.73   671.8 2148.13   681.8 2153.59   721.9 2178.72     752 2195.61
   902.4 2272.61   962.6 2300.28  1032.8 2330.18  1062.9 2342.03  1092.9  2352.1
#Mann= 3 , 0 , 0
       0      .1       0     528    .045       0  546.53      .1       0
Bank Sta=528,546.53
XS Rating Curve= 0 ,0
Exp/Cntr=0.3,0.1

Type RM Length L Ch R = 1 ,1893.9  ,868.2,860.7,853.2
XS GIS Cut Line= 2
     2154896.435      386463.279     2153993.433      387077.324
#Sta/Elev= 30
       0 2372.38   120.2 2306.18   170.3 2277.53   210.4 2256.36   280.5 2218.36
   320.6 2197.73   350.6 2183.52   370.7 2174.86   420.8 2155.61   510.9  2117.2
     531 2107.67     541  2103.9     551 2102.66     561 2103.85   581.1 2109.93
   591.1 2113.69   601.1 2118.31   641.2 2140.52   691.3 2169.63   761.4 2211.54
   781.4 2223.98   851.6 2269.72   871.6 2281.97   891.6 2293.03   921.7 2307.39
   961.8 2325.39  1031.9 2354.62  1041.9 2358.09    1072 2366.38    1092  2372.8
#Mann= 3 , 0 , 0
       0      .1       0     541    .045       0     561      .1       0
Bank Sta=541,561
XS Rating Curve= 0 ,0
Exp/Cntr=0.3,0.1

Type RM Length L Ch R = 1 ,1033.2  ,403,423.6,444.1
XS GIS Cut Line= 3
      2154453.67      385980.786     2153892.558      386108.945
     2153440.681      386713.937
#Sta/Elev= 30
       0 2354.85    60.6 2339.55    90.9 2330.14   151.5 2305.77   262.5 2258.09
     313 2241.95   343.3 2230.23   373.6 2221.53   424.1 2211.17   474.6 2198.24
   535.2 2178.94   545.3 2175.16   565.5 2165.62   575.6 2162.15   595.7 2158.21
   605.8 2155.17   666.2 2130.85   716.5  2106.9   746.7 2095.92   756.8  2094.7
   766.9 2096.36   776.9 2101.56   847.4 2146.48   968.2 2232.34   998.4  2251.8
  1038.7  2275.4    1089 2301.81  1149.4  2330.7  1270.3 2380.62  1330.7 2407.53
#Mann= 3 , 0 , 0
       0      .1       0   746.7    .045       0   766.9      .1       0
Bank Sta=746.7,766.9
XS Rating Curve= 0 ,0
Exp/Cntr=0.3,0.1

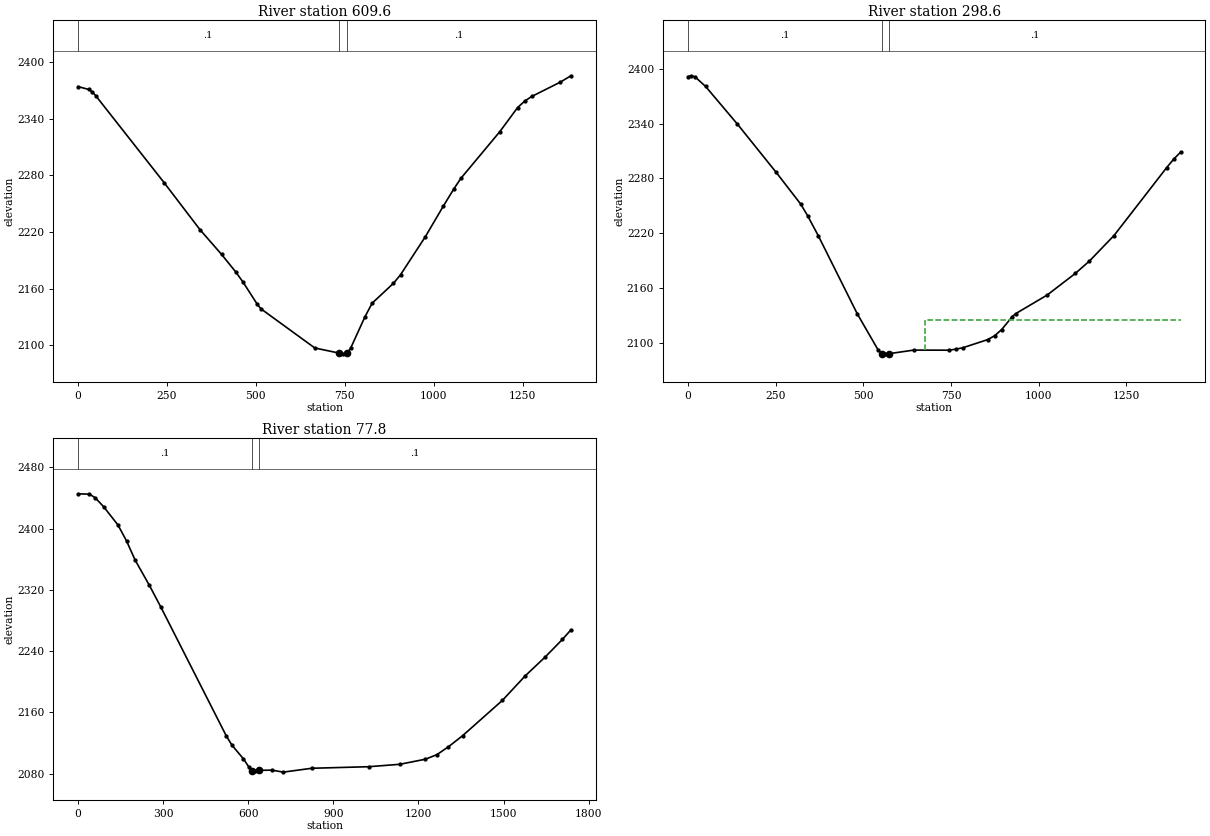
Type RM Length L Ch R = 1 ,609.6   ,301.8,311,320
XS GIS Cut Line= 3
     2154385.514      385899.812     2153558.526      385908.678
     2153239.427      386367.382
#Sta/Elev= 30
       0 2373.95    30.3 2370.89    40.3 2368.23    50.4 2363.97   242.1 2272.14
   342.9 2222.36   403.4 2196.26   443.8 2177.41     464 2166.83   504.3 2143.14
   514.4  2138.5   665.7 2097.06   732.5 2091.75   746.4 2090.54   756.4 2091.58
   766.5 2096.84   806.9 2130.21     827 2144.51   886.9 2165.58   906.9 2174.67
   976.7 2215.01  1026.6 2247.02  1056.5 2265.45  1076.5 2276.76  1186.2 2326.31
  1236.1 2351.77  1256.1 2358.63    1276 2363.55  1355.9 2378.64  1385.8 2385.36
#Mann= 3 , 0 , 0
       0      .1       0   732.5    .045       0   756.4      .1       0
Bank Sta=732.5,756.4
XS Rating Curve= 0 ,0
Exp/Cntr=0.3,0.1

Type RM Length L Ch R = 1 ,298.6   ,218.6,220.8,223
XS GIS Cut Line= 3
     2154366.245       385868.79     2153666.477      385616.276
     2153276.821      386150.495
#Sta/Elev= 30
       0 2391.29      10 2392.08    20.1    2391    50.3 2380.47   140.7 2339.48
   251.3 2286.76   321.7 2251.88   341.8 2238.89     372 2217.14   482.6 2132.28
   542.9 2092.26   552.9  2088.7     563 2088.14     573 2088.61   643.4 2092.53
   743.9 2092.44     764 2093.53     784 2095.14   854.1 2103.91   874.2 2108.16
   894.2 2114.84   924.3 2128.89   934.3 2132.31  1024.4 2152.72  1104.6 2176.31
  1144.7 2189.78  1214.8 2217.66  1365.1  2291.9  1385.1 2301.14  1405.2  2308.9
#Mann= 3 , 0 , 0
       0      .1       0   552.9    .045       0     573      .1       0
#XS Ineff= 2 , 0
                          676.02         2125.85
Permanent Ineff=
       F       F
Bank Sta=552.9,573
XS Rating Curve= 0 ,0
Exp/Cntr=0.3,0.1

Type RM Length L Ch R = 1 ,77.8    ,76.4,77.8,79.2
XS GIS Cut Line= 4
     2154515.822        385759.1     2153862.667       385447.48
     2153491.216      385529.748     2153202.032      386093.157
#Sta/Elev= 30
       0 2445.53    40.2 2445.09    60.3 2440.45    90.5 2428.55   140.7 2404.81
   170.9    2384     201 2359.13   251.3 2326.03   291.5 2297.84   522.7 2129.16
   542.8    2117     583  2099.3   603.1  2088.1   613.5 2083.91   623.2 2083.28
  638.65  2084.3   683.5 2084.52   723.7 2081.92   823.8 2086.96    1024 2088.99
  1134.3 2092.15  1224.8 2098.81    1265 2104.74  1305.2  2114.9  1355.4 2129.41
  1496.2 2175.74  1576.6 2207.74    1647  2232.4  1707.3 2255.22  1737.4 2267.73
#Mann= 3 , 0 , 0
       0      .1       0   613.5    .045       0  638.65      .1       0
Bank Sta=613.5,638.65
XS Rating Curve= 0 ,0
Exp/Cntr=0.3,0.1
Stream Node=RobbinsRun      ,Main            , 0 , 0 ,Upstream end
Stream Node=RobbinsRun      ,Main            , 0 , 1 ,Downstream end

Chan Stop Cuts=-1
Use User Specified Reach Order=0
Composite Channel Slope=5